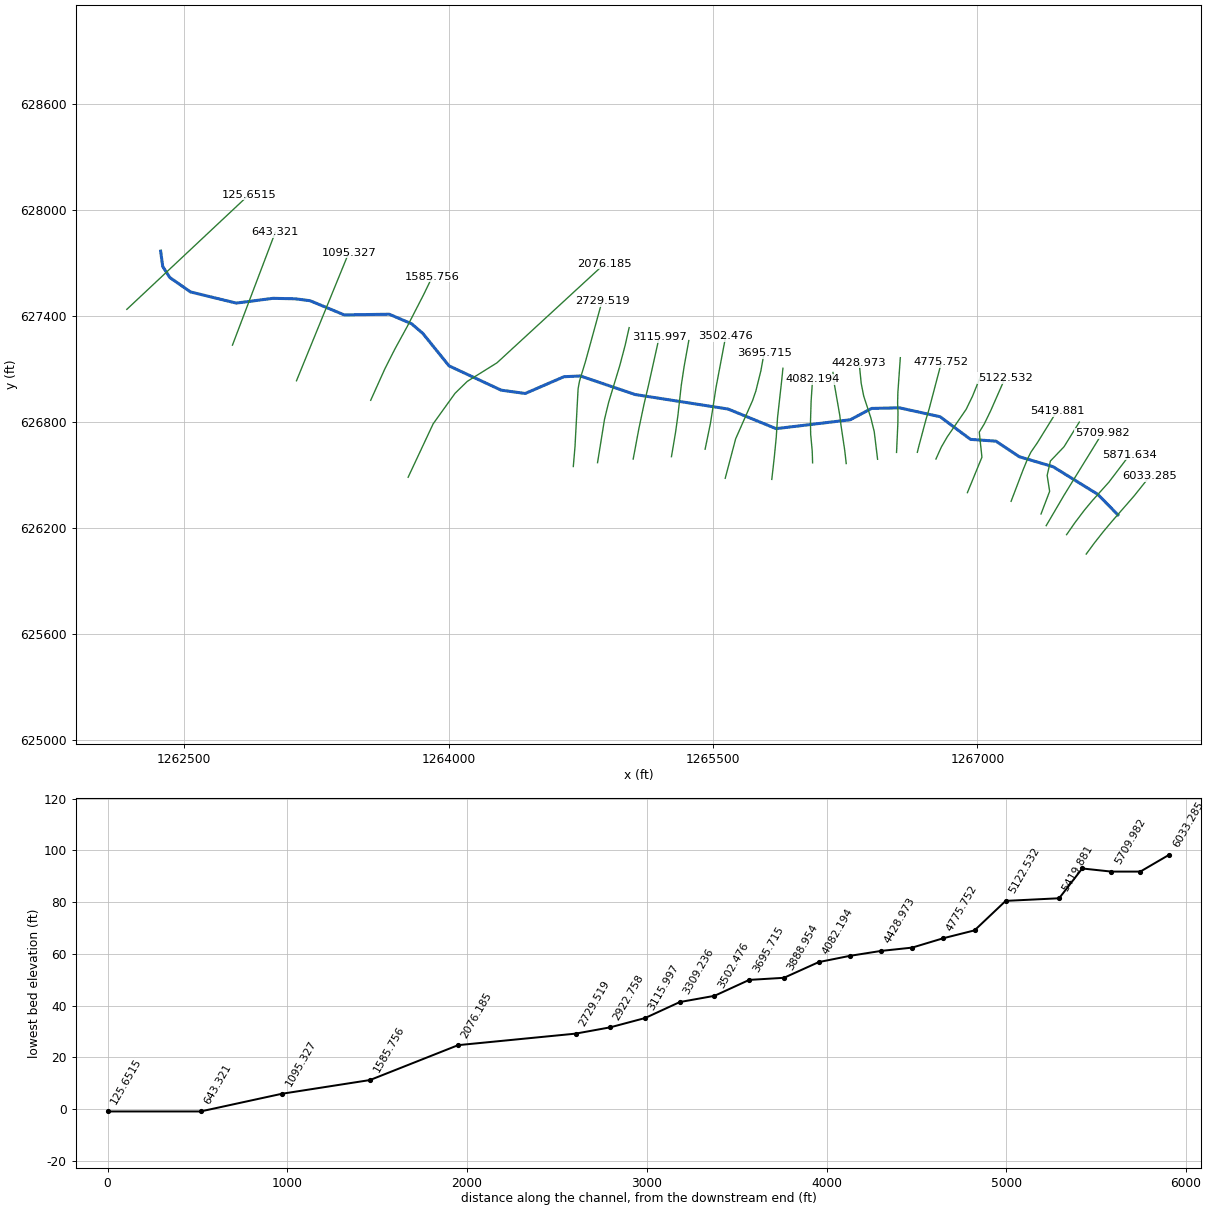
--- 628_ras.prj (project) ---

Proj Title=628
Current Plan=p01
Default Exp/Contr=0.3,0.1
English Units
Geom File=g01
Flow File=f01
Plan File=p01
Y Axis Title=Elevation
X Axis Title(PF)=Main Channel Distance
X Axis Title(XS)=Station
BEGIN DESCRIPTION:
RFD model 628 exported to HEC-RAS
END DESCRIPTION:

--- 628_ras.p01 (plan) ---

Plan Title=Plan 01
Program Version=4.10
Short Identifier=Plan 01
Geom File=g01
Flow File=f01
Subcritical Flow
Calc Critical at every XS
Secant Critical Depth

--- 628_ras.f01 (steady flow) ---

Flow Title=Flow 01
Program Version=5.01
Number of Profiles= 5
Profile Names=10yr,25yr,50yr,100yr,500yr
River Rch & RM=628,24,6033.285
  504.21  625.94  753.01  836.25 1032.68
River Rch & RM=628,24,5871.634
  508.83  632.52  761.16  846.44 1047.08
River Rch & RM=628,24,5709.982
  534.79  669.63  807.15  904.21 1129.15
River Rch & RM=628,24,5548.331
  542.68  680.97  821.21  921.96 1154.52
River Rch & RM=628,24,5419.881
  548.35  689.14  831.35  934.78 1172.88
River Rch & RM=628,24,5122.532
  580.19  735.18  888.56 1007.48 1277.71
River Rch & RM=628,24,4949.142
  581.59  737.22   891.1 1010.72 1282.41
River Rch & RM=628,24,4775.752
  608.24  776.07  939.45 1072.64 1372.59
River Rch & RM=628,24,4602.363
    1090    1514    1869    2326    3324
Boundary for River Rch & Prof#=628,24,1
Up Type= 0
Dn Type= 2
Boundary for River Rch & Prof#=628,24,2
Up Type= 0
Dn Type= 2
Boundary for River Rch & Prof#=628,24,2
Up Type= 0
Dn Type= 2
Boundary for River Rch & Prof#=628,24,2
Up Type= 0
Dn Type= 2
Boundary for River Rch & Prof#=628,24,2
Up Type= 0
Dn Type= 2

--- 628_ras.g01 (geometry) ---

Geom Title=628
Program Version=4.10

River Reach=628,24
Reach XY= 30
 1267797.2641139626275.9404443071267682.80134056626392.111623894
1267429.10399657626548.4301993211267237.76323702626604.807393421
1267105.36226643 626692.789979281266961.00249603626703.040381402
1266788.45413477626831.1703602121266557.82018302626881.568156651
1266399.79321495626878.1513619931266279.35103754626814.086378634
1265858.23052146626763.6886012631265585.74077996626874.734586497
1265058.69948924626956.7377851591264747.77075536 627061.80437278
 1264654.6629741627057.5333763291264435.13361588626962.717202177
1264298.46164413626981.5096023131264002.90850809627119.035782836
1263853.42354384627303.5429494731263790.21275822627357.357540292
1263663.53222064 627411.254895471263408.47488185627407.457566851
1263214.59499515 627487.714828741263130.73067137627498.536034276
1263003.58153495627501.2413387521262796.17514126627474.188337128
1262536.46626855627537.3120293661262418.33480366627619.372822911
1262378.65706076627681.5947418441262366.93409331627768.164366893

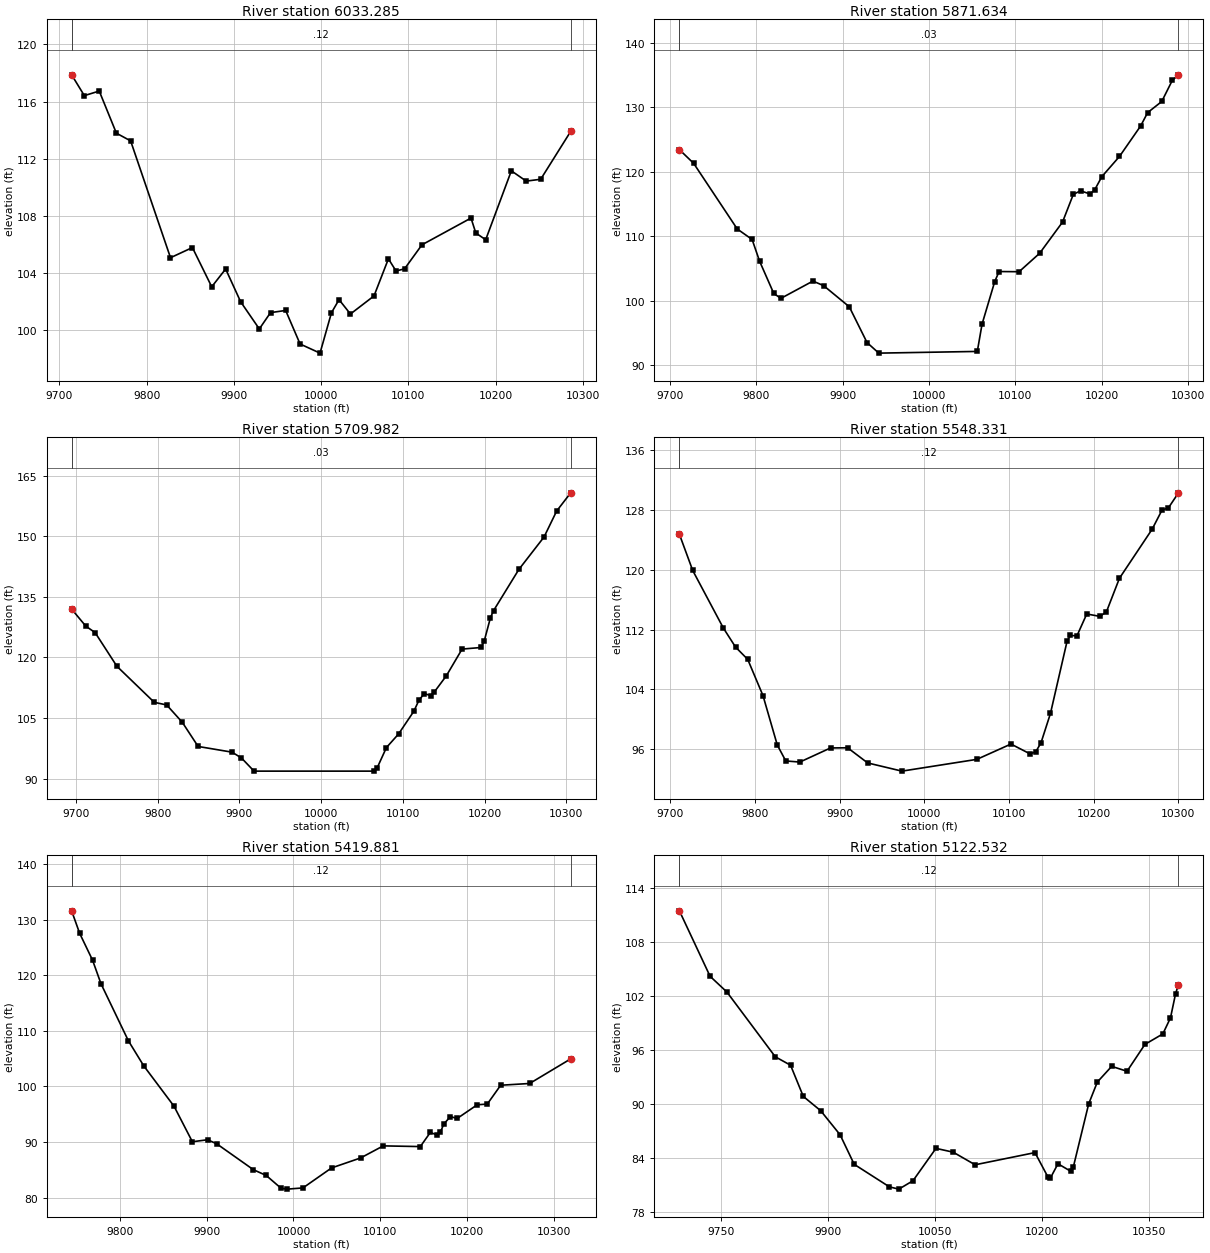
Type RM Length L Ch R = 1 ,6033.285,161.651400,161.651400,161.651400
XS GIS Cut Line= 6
1267617.37276931626053.9349971841267664.97354512626118.358480404
1267713.13672425626179.2634667371267763.41669423626239.091164843
1267889.07538021626382.803564753 1267979.7146156626496.058095989
#Sta/Elev= 30
9714.065117.87329728.636116.4178 9745.71116.73889765.349113.79139781.666113.2524
9827.358105.07929852.455105.78979874.582103.04439890.549104.28939907.691102.0014
9929.119100.09619941.976101.23789959.308101.38939975.843 99.04279998.67998.40409
10011.77101.227910020.47 102.14510033.52101.140510060.54102.406610077.04 105.001
10085.74104.1521 10095.5104.298810115.48105.981910171.68107.852810177.18106.8065
10188.49106.3363 10217.9111.158110234.94110.437810251.52110.566710285.92113.9168
#Mann= 3 , 0 , 0
9714.065    0.12       09714.065    0.12       010285.92    0.12       0
#XS Ineff= 2 , 0
       09969.471        10034.93       0
Bank Sta=9714.065,10285.92
Exp/Cntr=0.3,0.1

Type RM Length L Ch R = 1 ,5871.634,161.651400,161.651400,161.651400
XS GIS Cut Line= 6
1267506.00453236 626163.654088491267554.20102791626232.745621732
1267607.57198708626303.0870293691267650.04013243626353.957230353
1267746.21049838 626461.054310061267864.29119398626616.032509268
#Sta/Elev= 30
9711.171123.4367 9727.69121.30579778.132111.11539795.335109.48679803.938106.1286
9820.412 101.0989828.648100.34069865.713103.02499878.068102.31969907.77299.03887
9928.34693.478949941.96391.8372710055.97 92.100710061.4896.3453910076.13102.9445
10081.17104.507410104.35104.480610128.14107.342910154.58112.1772 10167.1116.4894
10175.47117.045810186.49116.546210191.95117.223610200.11119.2419 10220.5122.3757
10244.97127.102710253.13129.185810269.44130.914810281.67134.193910288.83135.0549
#Mann= 3 , 0 , 0
9711.171    0.03       09711.171    0.03       010288.83    0.03       0
#XS Ineff= 2 , 0
       09930.413        10042.88       0
Bank Sta=9711.171,10288.83
Exp/Cntr=0.3,0.1

Type RM Length L Ch R = 1 ,5709.982,161.651400,161.651400,161.651400
XS GIS Cut Line= 5
1267390.42606649626214.747847068 1267491.3573175626386.431375669
1267546.52167161626475.9075421791267547.57987424626477.604659497
1267707.56023053626736.427250333
#Sta/Elev= 30
9694.731131.9522 9712.07127.73279723.488126.12719750.128117.79329795.798108.8753
9811.021 108.2189830.064103.94049849.48597.943299890.94296.532789902.468 95.0984
9917.88591.83727 10064.491.8372710068.2592.5333810079.83 97.671610094.63101.0213
10113.35106.654210119.59109.381410126.11 111.02410133.82 110.55510138.31 111.405
10153.11115.431510172.39122.049210195.53122.443910199.39123.987910207.11129.8444
10210.96131.594210241.82141.762310272.67149.8078 10288.1 156.23710305.27160.7338
#Mann= 3 , 0 , 0
9694.731    0.03       09694.731    0.03       010305.27    0.03       0
#XS Ineff= 2 , 0
       09911.889        10085.75       0
Bank Sta=9694.731,10305.27
Exp/Cntr=0.3,0.1

Type RM Length L Ch R = 1 ,5548.331,128.450300,128.450300,128.450300
XS GIS Cut Line= 6
1267361.10014698626281.0134275261267409.92827201626409.051621959
1267395.82236925626499.112385854 1267414.2685498626580.492594182
1267491.45822653626661.102814168 1267578.1140359626800.761691406
#Sta/Elev= 30
 9710.66 124.7689726.391119.91819762.488112.22519776.927 109.6669791.366108.0083
9809.414 103.1499826.29596.532489836.29994.408719852.90294.260279889.13896.14917
9909.38296.17141    993394.142349973.48893.0456610061.9894.6217210102.2696.67326
10124.6695.3636610131.4295.61534 10137.796.8337210148.88100.769310168.59110.4811
10172.45 111.21610180.17111.165710191.76114.0935 10207.2113.773410214.92114.3593
10230.37118.876110268.98125.444710280.56127.991610288.28128.3198 10300.1 130.318
#Mann= 3 , 0 , 0
 9710.66    0.12       0 9710.66    0.12       0 10300.1    0.12       0
#XS Ineff= 2 , 0
       09923.689        10076.46       0
Bank Sta=9710.66,10300.1
Exp/Cntr=0.3,0.1

Type RM Length L Ch R = 1 ,5419.881,297.349000,297.349000,297.349000
XS GIS Cut Line= 6
 1267191.2144179626352.2561039921267259.75598937 626531.76082471
1267284.40041047626591.6129327271267303.96227032626631.125551611
1267339.39875811626682.489121944 1267451.1609109 626862.61064972
#Sta/Elev= 30
 9744.22131.61859753.504127.56069768.364122.73219778.087118.48669809.694108.2107
9827.253103.73639862.37296.417289883.44390.040539901.002 90.40129911.53889.67012
9953.85985.003669968.53883.976449985.79181.658269992.88881.5119210010.9381.72906
10043.8885.3251510077.4187.1257710103.5289.2997110146.2489.1728310157.82 91.7239
10165.5491.25299 10169.491.7378810173.2693.2273910180.9994.5742110188.7194.23021
10211.8796.6990410223.4696.82527 10238.9100.216910272.31100.533310319.65 104.963
#Mann= 3 , 0 , 0
 9744.22    0.12       0 9744.22    0.12       010319.65    0.12       0
#XS Ineff= 2 , 0
       09930.061        10094.47       0
Bank Sta=9744.22,10319.65
Exp/Cntr=0.3,0.1

Type RM Length L Ch R = 1 ,5122.532,173.389700,173.389700,173.389700
XS GIS Cut Line= 6
1266943.34841087626401.4561358391267025.81368867626602.193983063
1267010.69113871 626743.872808741267039.17308941626790.406661347
1267075.71432191626865.5515413581267157.10709146 627050.32766363
#Sta/Elev= 30
9691.754111.45729734.776 104.1759758.336102.42789826.17895.222479847.60294.28404
9865.45590.813969889.90189.218199917.03786.548189936.80683.26016 9986.2380.75092
 9999.4180.5009510019.21 81.431510051.4585.03546 10075.684.6105410106.3583.20897
10190.25 84.562810208.1781.8887410211.7681.7197810222.5183.3216710240.4482.48504
10244.02 82.955310265.5389.97527 10277.792.41425 10297.894.1572410319.3193.61119
 10344.496.59987 10369.5 97.764810380.2599.5531210387.42102.252610391.47103.2426
#Mann= 3 , 0 , 0
9691.754    0.12       09691.754    0.12       010391.47    0.12       0
#XS Ineff= 2 , 0
       09944.485        10051.08       0
Bank Sta=9691.754,10391.47
Exp/Cntr=0.3,0.1

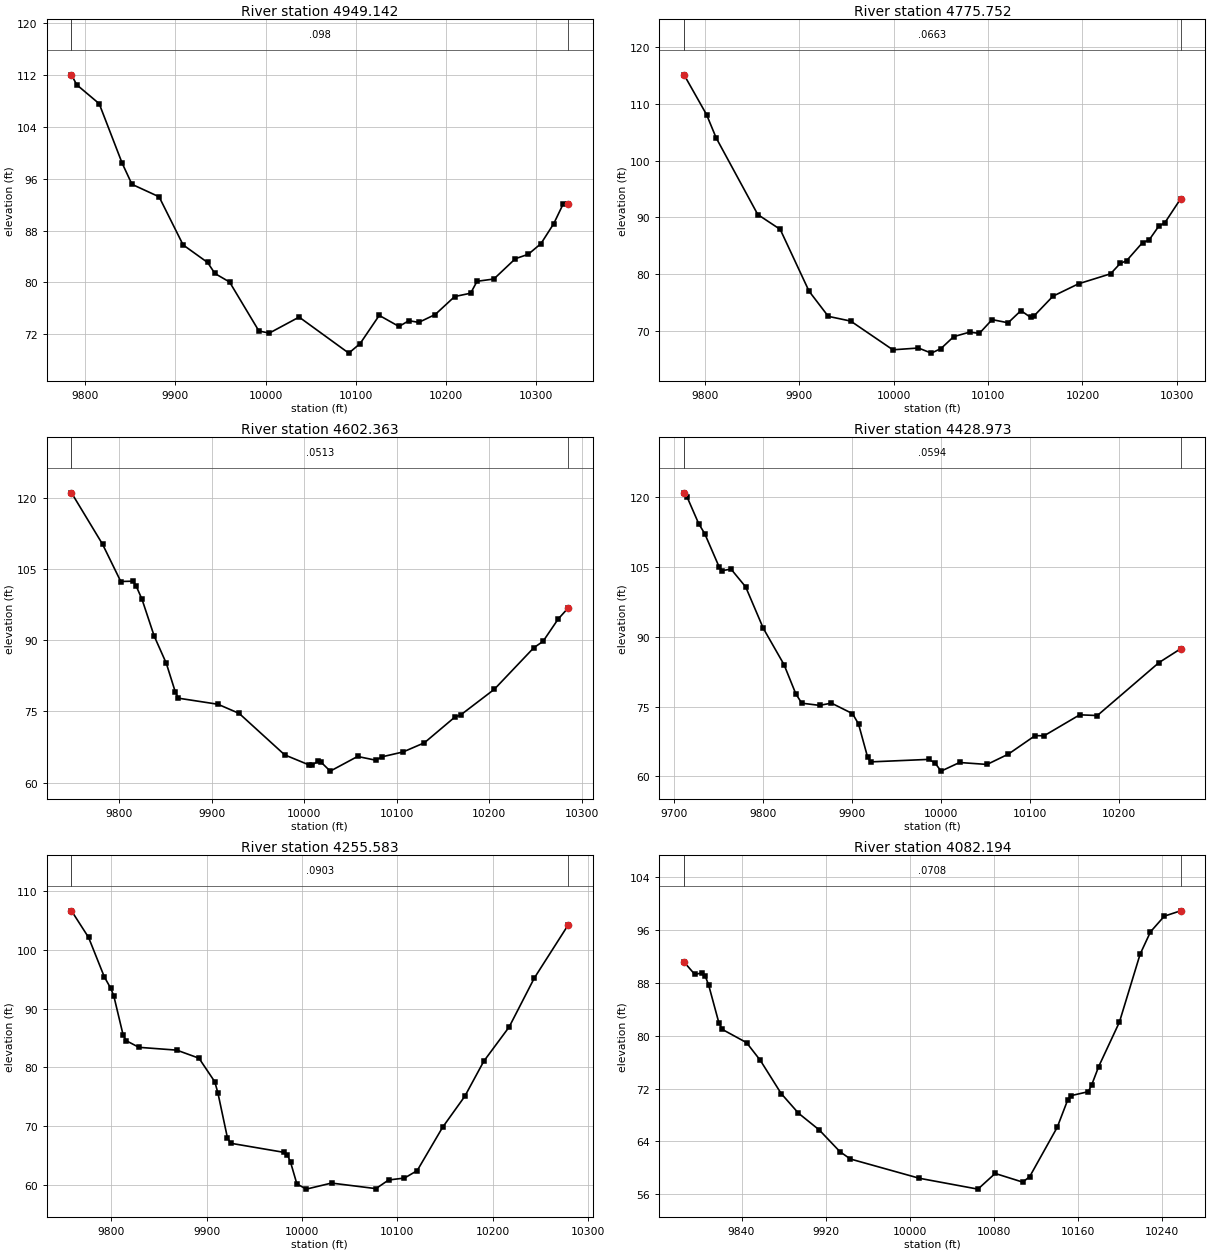
Type RM Length L Ch R = 1 ,4949.142,173.389600,173.389600,173.389600
XS GIS Cut Line= 6
1266764.97564163  626591.80538871266795.43088377626659.411591332
1266829.75694758  626718.19926791266936.19164544626872.818337582
1266972.71719916626947.9815360771267024.06410553627074.373045113
#Sta/Elev= 30
9784.968112.04699790.751 110.5129815.668 107.5899841.07398.413949851.96195.14469
9882.01893.219269908.612 85.79099935.75483.078629943.87281.379689960.109   80.06
9992.58472.50305 10004.1 72.176710037.1574.6490610092.15 69.085310104.7270.55403
10125.9174.9115710147.7973.2009610158.74 74.093610169.6873.8300710187.9275.04522
10209.4877.8197210227.1878.3369910234.2780.1754510252.8780.5249310276.7683.66743
10290.9384.3339910305.0985.9903410319.2689.0770910329.8892.1658510335.0492.17739
#Mann= 3 , 0 , 0
9784.968   0.098       09784.968   0.098       010335.04   0.098       0
#XS Ineff= 2 , 0
       09980.583         10035.8       0
Bank Sta=9784.968,10335.04
Exp/Cntr=0.3,0.1

Type RM Length L Ch R = 1 ,4775.752,173.389700,173.389700,173.389700
XS GIS Cut Line= 6
1266659.39017725626629.7692863581266667.77390401626663.832652757
1266708.79789229626816.9702635471266717.47162759626845.350159516
1266726.11098722626874.5315772781266795.64313882 627138.06755804
#Sta/Elev= 30
9777.706115.16619801.551108.14099811.687 104.0489855.83690.507159879.61287.88697
 9910.1876.981339930.55972.540459954.33571.70391    999966.6362710026.1466.95175
10039.7666.0498210049.9466.8455510063.5168.9616810080.4869.7572110090.6669.53069
10104.2371.9647510121.1971.4026310134.7773.5549510144.9472.3614810148.34 72.5614
 10168.776.0977510195.8478.2894510229.7780.0486510239.9581.8720610246.74 82.3576
 10263.785.5667410270.4985.9867210280.6788.4063910287.4689.1006210303.9993.27084
#Mann= 3 , 0 , 0
9777.706  0.0663       09777.706  0.0663       010303.99  0.0663       0
#XS Ineff= 2 , 0
       0  9963.7        10077.65       0
Bank Sta=9777.706,10303.99
Exp/Cntr=0.3,0.1

Type RM Length L Ch R = 1 ,4602.363,173.389700,173.389700,173.389700
XS GIS Cut Line= 6
1266541.45999898626629.2437902521266548.86966783626792.914359329
1266549.70193653626856.9017237641266547.46225491626909.382744823
1266548.91109292626966.9091028611266562.92206393627165.422271786
#Sta/Elev= 30
 9748.29121.06029781.877110.22889801.592102.37259814.725102.44429818.008101.5223
9824.57598.607369837.70890.882819850.84185.122269860.69179.016699863.97477.78426
9906.65776.506379929.62874.574699978.84765.8389610005.1263.7282510008.4163.67863
10014.9764.5246810018.2664.2801310028.11 62.414910057.6465.5052710077.3464.71797
 10083.965.42182 10106.966.4572510129.9168.3865410162.7773.7893110169.3474.27562
10205.5379.6577410248.3388.43288 10258.289.7483410274.6694.4803410285.2396.75526
#Mann= 3 , 0 , 0
 9748.29  0.0513       0 9748.29  0.0513       010285.23  0.0513       0
#XS Ineff= 2 , 0
       09954.477                       0
Bank Sta=9748.29,10285.23
Exp/Cntr=0.3,0.1

Type RM Length L Ch R = 1 ,4428.973,173.389600,173.389600,173.389600
XS GIS Cut Line= 6
1266433.89920427626590.4616396021266414.86817194626746.746282434
 1266395.3177776626825.9377750771266355.28654789626947.654509338
1266340.99999226627019.6417410531266329.32088013627136.445372332
#Sta/Elev= 30
9711.038120.95749714.456120.04539727.627114.26079734.213112.20389750.676104.9308
9753.969104.23959763.847104.55289780.311100.72679800.11891.82254 9823.3984.02713
9836.68777.734689843.33675.738369863.28375.267389876.71375.747229900.36873.49073
9907.12771.282519917.265 64.19669920.64463.116759986.01163.655749992.99562.91698
9999.94961.1317110020.7162.9867510051.6562.5683710075.5264.7815810105.6768.76483
10115.71 68.7245 10155.873.2359410175.6473.0849110244.9484.46876 10269.287.42478
#Mann= 3 , 0 , 0
9711.038  0.0594       09711.038  0.0594       0 10269.2  0.0594       0
#XS Ineff= 2 , 0
       09901.272                       0
Bank Sta=9711.038,10269.2
Exp/Cntr=0.3,0.1

Type RM Length L Ch R = 1 ,4255.583,173.389700,173.389700,173.389700
XS GIS Cut Line= 6
1266255.99977292626566.2060770531266247.86253693626638.243460526
1266226.40606067626782.2420111571266219.23292573626840.157905482
1266190.10372103627006.5756954011266180.84213836 627081.71874605
#Sta/Elev= 30
9758.043106.69649775.975102.15639792.48495.431619799.087 93.52829802.38992.21953
9812.29485.473279815.59584.533059828.80283.413789868.59982.932189891.81881.56103
9908.40377.547329911.72175.627039921.67268.000499924.98967.053769981.35865.48894
9984.66265.074629987.96663.808329994.57460.1215710004.4859.2252910030.9560.25905
10077.5559.3112410090.88 60.786310107.53 61.114510120.8562.38075 10147.569.76431
10170.8175.05542 10190.881.0488110217.3586.8754710243.8195.2368510279.15104.2388
#Mann= 3 , 0 , 0
9758.043  0.0903       09758.043  0.0903       010279.15  0.0903       0
#XS Ineff= 2 , 0
       0 9928.04                       0
Bank Sta=9758.043,10279.15
Exp/Cntr=0.3,0.1

Type RM Length L Ch R = 1 ,4082.194,193.239300,193.239300,193.239300
XS GIS Cut Line= 6
1266065.28106183626570.4885348681266063.09752864 626637.03252393
 1266054.2946001626732.0303152651266053.20765737626799.233813062
1266056.83857808626919.2861757131266065.04443175 627042.41961965
#Sta/Elev= 30
9785.31291.110379795.573 89.23419802.13889.471789805.42189.005189808.70487.64395
9818.55181.869589821.83480.923989844.81278.934139857.96976.241549877.75271.24489
9894.23868.273529914.00365.744329933.75962.453229943.63761.3540110009.2858.44401
10065.0756.8025910081.4859.1704810107.7457.8612810114.3158.6780510140.5866.14815
10150.4470.2332810153.7370.9257610170.1771.5262210173.4672.5842410180.0375.31683
10199.7682.0291910219.49  92.30410229.3695.6778610242.5198.0443810258.0298.85095
#Mann= 3 , 0 , 0
9785.312  0.0708       09785.312  0.0708       010258.02  0.0708       0
#XS Ineff= 2 , 0
       09925.443                       0
Bank Sta=9785.312,10258.02
Exp/Cntr=0.3,0.1

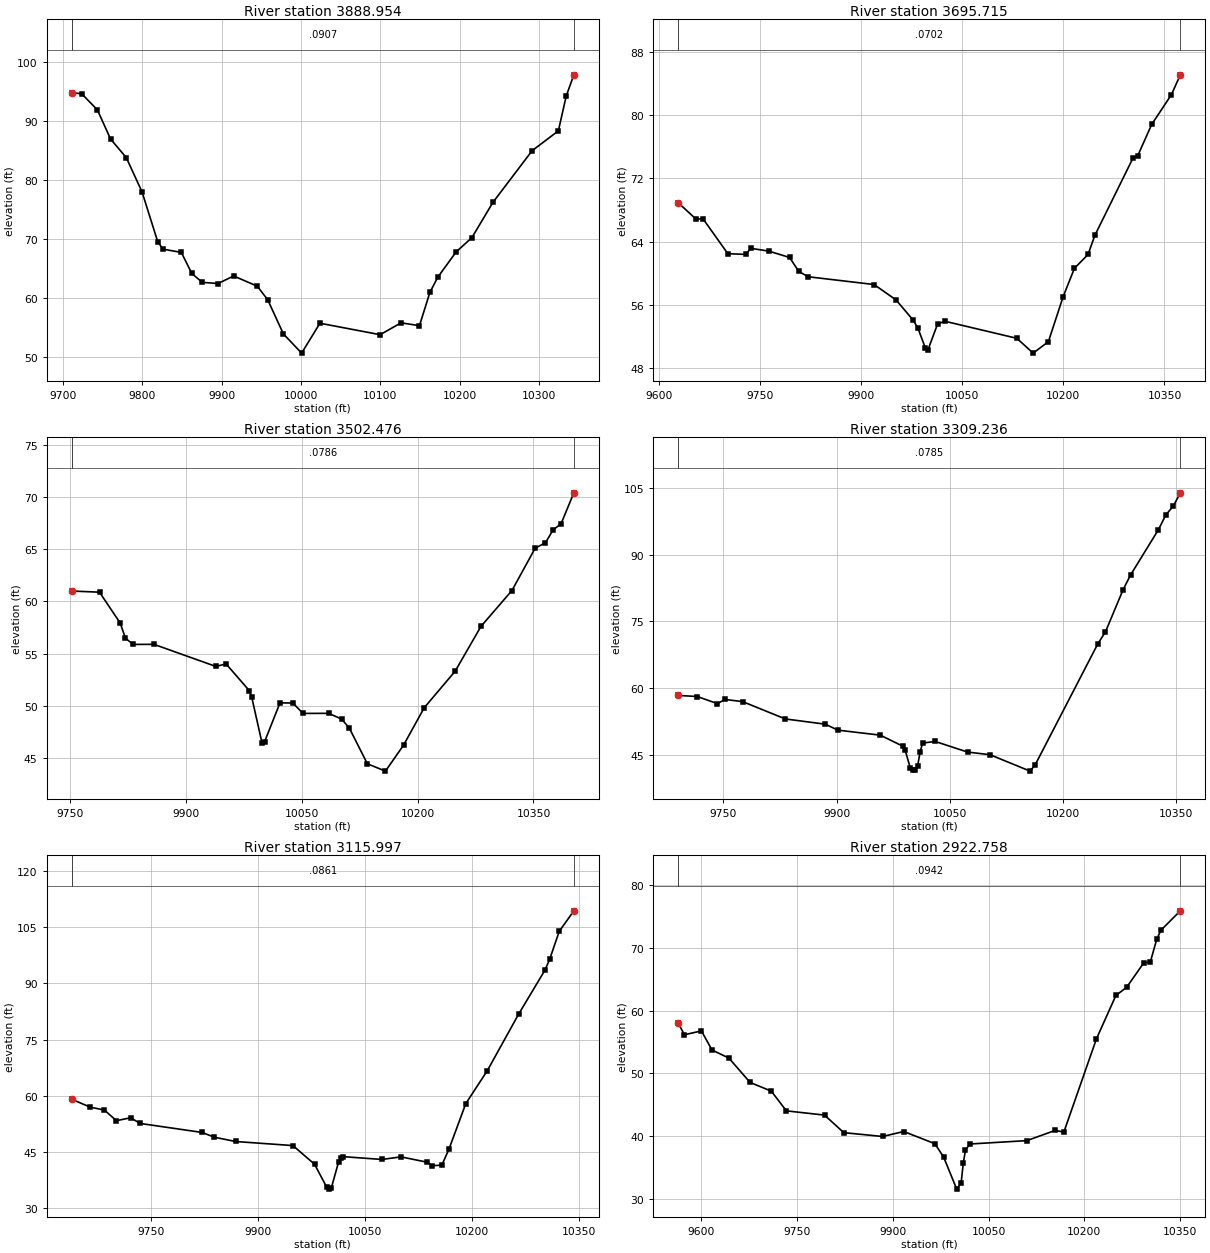
Type RM Length L Ch R = 1 ,3888.954,193.239300,193.239300,193.239300
XS GIS Cut Line= 6
1265833.75748301626476.4605648961265847.65556972626598.822017712
1265858.99303393626714.212484412 1265866.1521461626823.791663912
1265889.69258422627033.8874713851265896.95019396627105.384703144
#Sta/Elev= 30
9711.41194.792289723.91294.620639743.72391.881159760.23386.956439780.045 83.8196
9799.85678.018099819.66869.575949826.27268.321689849.36167.769389862.54864.21121
9875.73462.700999895.51462.508979915.29463.783399944.96462.057029958.12859.76141
9977.84953.9812410000.8550.7293610023.8855.7884510099.6753.8499510126.0855.85841
10149.19 55.3741 10162.461.02388 10172.363.5802410195.41  67.85910215.2270.26906
10241.6376.2252910291.1384.9924310324.1188.34052   10334 94.2358 10343.697.82192
#Mann= 3 , 0 , 0
9711.411  0.0907       09711.411  0.0907       0 10343.6  0.0907       0
#XS Ineff= 2 , 0
       09927.726                       0
Bank Sta=9711.411,10343.6
Exp/Cntr=0.3,0.1

Type RM Length L Ch R = 1 ,3695.715,193.239300,193.239300,193.239300
XS GIS Cut Line= 6
1265569.53444978626482.7069231411265628.87392366 626706.44826208
1265724.48655862626922.2339916341265743.53918036626977.361937375
 1265772.1888673627092.5506323431265789.79257303627190.855975542
#Sta/Elev= 30
9628.79768.929829655.29466.853929665.37966.921629702.35962.493219729.44562.40057
9736.23363.171969763.38662.812159793.93462.012129807.64960.245339821.43259.57538
9919.26258.591319951.88156.643719977.25154.08533  9984.5 53.03369995.373  50.554
9998.99750.2874110013.5253.6105510024.4353.9451110130.96 51.792510155.2549.91741
10177.8451.3685210199.5357.0177410216.4260.6377310236.6162.39281 10246.764.79834
10303.6374.64405 10310.374.8661510331.0278.8316910360.3382.6077410373.4885.10819
#Mann= 3 , 0 , 0
9628.797  0.0702       09628.797  0.0702       010373.48  0.0702       0
#XS Ineff= 2 , 0
       09907.498                       0
Bank Sta=9628.797,10373.48
Exp/Cntr=0.3,0.1

Type RM Length L Ch R = 1 ,3502.476,193.239200,193.239200,193.239200
XS GIS Cut Line= 6
1265455.52340588626647.2961102871265485.99428707626794.884575856
 1265500.8424084626889.2667444191265501.09745195626891.250415963
1265517.06286312626995.1333873651265572.21227543627286.076343174
#Sta/Elev= 30
9752.75660.984919788.651 60.87599815.45257.914319822.15256.472929832.20255.87663
9859.00255.885899939.09353.771769952.37854.011399982.26951.46485 9985.5950.81738
9998.87446.4466210002.1946.56745 10022.150.28921 10038.7 50.267210051.9849.27463
10085.1749.2828710101.7748.7352310111.7647.8786810135.1344.4563910158.5143.75325
10181.8846.22842 10208.649.8111310248.6753.3115510282.0657.5993810322.1461.03421
10352.1965.0824810365.5565.6097710375.5666.8568810385.5867.4021610402.2370.38257
#Mann= 3 , 0 , 0
9752.756  0.0786       09752.756  0.0786       010402.23  0.0786       0
#XS Ineff= 2 , 0
       09900.331                       0
Bank Sta=9752.756,10402.23
Exp/Cntr=0.3,0.1

Type RM Length L Ch R = 1 ,3309.236,193.239300,193.239300,193.239300
XS GIS Cut Line= 6
1265264.59396411626605.0057244861265287.77834587626742.399002584
1265301.30652522626838.9452823351265320.04836355627007.249777507
1265336.38233547627115.0930100571265362.95002031627262.265116753
#Sta/Elev= 30
9690.38258.36303  9715.758.116159742.31456.515089752.29557.457489775.58356.97385
9832.12853.074419885.13551.896049901.69950.556139957.90549.430689987.61146.95861
9990.91146.031919997.51342.1061310000.8241.5733510004.1241.5992310007.4242.56287
10010.73 45.741210014.0347.6521810030.5348.0124410073.45 45.627810103.1945.03088
10156.2841.3402610162.9242.7260310246.0769.9993110256.0772.6584210279.4182.13848
10289.4185.4750110326.0895.6028810336.0898.9733610346.08100.988810355.18103.9218
#Mann= 3 , 0 , 0
9690.382  0.0785       09690.382  0.0785       010355.18  0.0785       0
#XS Ineff= 2 , 0
       09914.805                       0
Bank Sta=9690.382,10355.18
Exp/Cntr=0.3,0.1

Type RM Length L Ch R = 1 ,3115.997,193.239300,193.239300,193.239300
XS GIS Cut Line= 6
1265047.49661569 626591.467161691265079.54721874 626762.59104217
1265109.59962834626904.9125799641265132.04428993 626998.72600664
1265185.38411642627238.4712031041265193.98268929627279.971165222
#Sta/Elev= 30
9638.91759.089199664.72457.006739684.75256.219949701.44153.386929721.46854.16973
 9734.8252.652619821.64450.25735 9838.41 49.00179868.58947.842549949.06546.75383
9979.366 41.7782 9996.2335.708949999.60635.1445210002.9935.5381210013.1142.42897
10016.4843.5467410019.8543.7993710073.7643.0554510100.6443.7427910137.6242.31024
10144.3441.4100510157.7841.5133510167.8745.8357810191.3957.9403510221.6466.74543
10265.3481.73992 10302.393.48826   10309 96.398910322.41103.856910342.93  109.34
#Mann= 3 , 0 , 0
9638.917  0.0861       09638.917  0.0861       010342.93  0.0861       0
#XS Ineff= 2 , 0
       09911.795                       0
Bank Sta=9638.917,10342.93
Exp/Cntr=0.3,0.1

Type RM Length L Ch R = 1 ,2922.758,193.239300,193.239300,193.239300
XS GIS Cut Line= 6
1264845.30017337626571.0854473831264884.86801645626816.575413804
1264908.36772275 626913.084027741264971.19106981627119.749622473
1265001.89109609627235.269951161 1265024.5404829627335.289979074
#Sta/Elev= 30
9564.10257.99921 9573.8656.157049600.37556.777489616.94653.733229643.46152.43712
9676.62348.561599709.85647.173929733.43544.034559793.15643.357069823.334 40.5626
9884.11439.95097 9917.1540.745299965.90438.805049979.601 36.682910000.1531.56488
10007.0232.5213810010.4535.7538210013.8837.8016510020.75 38.754310109.9839.29246
10154.3140.9223310167.8940.6505310218.8155.4863210249.3562.4153210266.1763.71816
10293.0867.6282310303.1767.7098610313.2671.3611810319.9972.8245910350.2275.90215
#Mann= 3 , 0 , 0
9564.102  0.0942       09564.102  0.0942       010350.22  0.0942       0
#XS Ineff= 2 , 0
       09940.571        10161.46       0
Bank Sta=9564.102,10350.22
Exp/Cntr=0.3,0.1

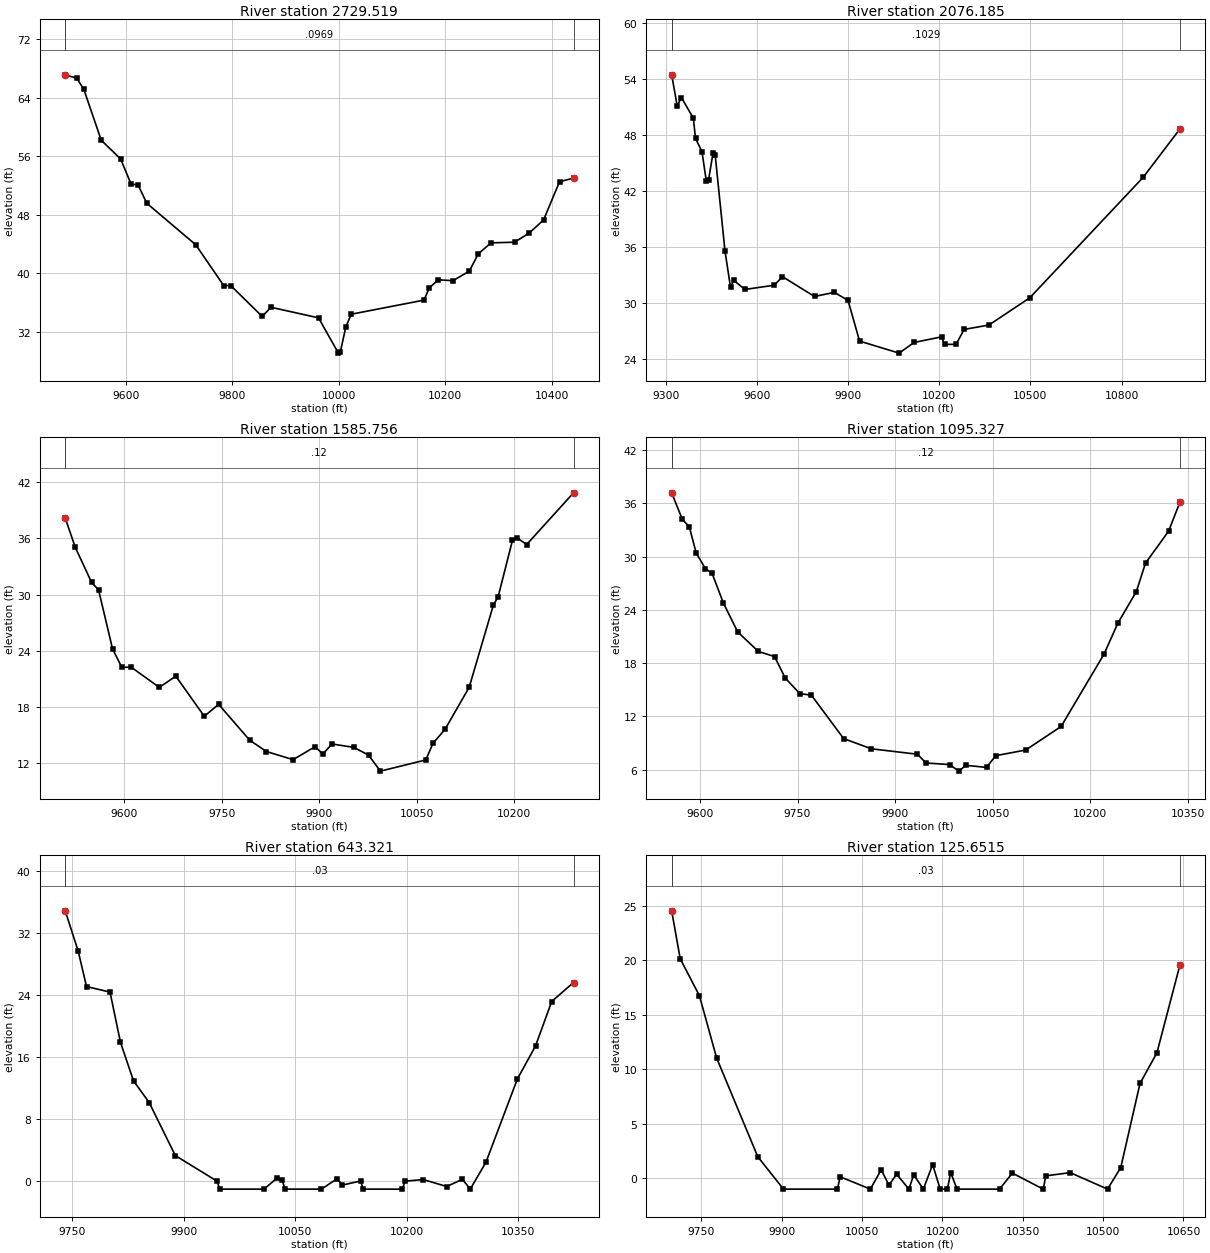
Type RM Length L Ch R = 1 ,2729.519,653.333500,653.333500,653.333500
XS GIS Cut Line= 6
1264707.80828354626549.3151894661264717.39201909626661.232182413
1264735.01427096626989.5371627211264743.04139569  627032.8980086
1264777.11577198627144.5116913911264870.86577198627484.789469182
#Sta/Elev= 30
9486.08267.126959507.74866.66425 9520.9265.167559553.84858.181369590.06955.65178
9609.80452.20938 9622.95 52.08289639.38349.58513 9731.3643.911029783.89138.34025
9797.02438.346379856.12134.130779872.57835.379629961.94633.937619999.29829.11841
10002.79 29.214910013.0832.6516510023.3634.4308810160.0836.3574610170.2938.06613
 10187.3 39.129310214.5339.0110210245.1640.3156910262.17 42.689510285.9944.17707
10330.23 44.269610357.4645.5032810384.6847.3027910414.6952.5300410441.0153.01789
#Mann= 3 , 0 , 0
9486.082  0.0969       09486.082  0.0969       010441.01  0.0969       0
#XS Ineff= 2 , 0
       09869.276        10113.81       0
Bank Sta=9486.082,10441.01
Exp/Cntr=0.3,0.1

Type RM Length L Ch R = 1 ,2076.185,490.429000,490.429000,490.429000
XS GIS Cut Line= 6
1263770.84300402626488.6108077021263912.96118233626791.305637047
1264036.76541871626963.4956996141264106.50073764627031.362173513
1264274.94563311 627136.265163631264886.74290952627698.245436028
#Sta/Elev= 30
9318.687 54.48329336.74951.179649350.96452.042649390.05549.834689397.162 47.6726
9418.48546.247169432.82243.081939440.05643.201329454.52646.06086 9461.7645.94122
9494.31735.585569512.403 31.72229523.25532.457849559.57431.485859656.50431.93939
 9683.46 32.85719788.97130.73234 9854.36 31.17379899.44530.309739937.35425.95263
 10067.524.6623710116.9625.80725 10207.626.4073610217.12 25.601110255.17 25.6042
10281.6827.2025410363.2527.6720510497.7430.5884110871.0343.4962910992.4248.69065
#Mann= 3 , 0 , 0
9318.687  0.1029       09318.687  0.1029       010992.42  0.1029       0
#XS Ineff= 2 , 0
       09962.849        10228.59       0
Bank Sta=9318.687,10992.42
Exp/Cntr=0.3,0.1

Type RM Length L Ch R = 1 ,1585.756,490.429000,490.429000,490.429000
XS GIS Cut Line= 6
1263558.56021231626924.2079911981263638.80693838627102.146794677
1263695.42822254627213.6926626121263766.90605038627343.845639005
1263859.84674999627524.3172509521263907.87049407 627623.32058087
#Sta/Elev= 30
9509.413 38.16549524.85735.040849549.92631.297889560.67130.501889582.15924.21512
9596.48522.22819 9610.8122.253099654.19520.092019679.54821.289629723.30217.00915
9745.37818.284079793.20914.453339818.96413.248479859.95112.381429893.63813.76288
9905.66412.982619919.83914.052699953.37413.691729975.98512.865669994.21711.15801
   1006412.3521810075.1314.1282810093.6815.6250710130.7820.1057210167.8828.85171
 10175.329.7582410197.2835.76492   1020436.0674610219.1535.3314510291.2740.84808
#Mann= 3 , 0 , 0
9509.413    0.12       09509.413    0.12       010291.27    0.12       0
#XS Ineff= 2 , 0
       09771.703                       0
Bank Sta=9509.413,10291.27
Exp/Cntr=0.3,0.1

Type RM Length L Ch R = 1 ,1095.327,452.006100,452.006100,452.006100
XS GIS Cut Line= 2
1263137.57584143 627034.702663631263433.79979977627758.443983063
#Sta/Elev= 30
9556.40837.200789572.83334.198119583.46833.389599594.10330.430579608.28328.65486
9618.56728.133569635.88924.801629657.91321.533179689.81819.321599714.63318.75111
9731.16316.326679753.62914.571529771.35414.400999820.9849.5073869863.5248.358868
9934.4247.7441889947.6946.7580359984.0546.5814549998.2345.84168310008.876.496021
10040.776.26162410054.957.58425610101.048.21801110155.5610.8778410221.5719.02889
10242.8422.51317 10271.226.0620910285.3829.2821210320.8332.8684810338.4336.16864
#Mann= 3 , 0 , 0
9556.408    0.12       09556.408    0.12       010338.43    0.12       0
#XS Ineff= 2 , 0
       09866.472                       0
Bank Sta=9556.408,10338.43
Exp/Cntr=0.3,0.1

Type RM Length L Ch R = 1 , 643.321,517.669500,517.669500,517.669500
XS GIS Cut Line= 2
1262774.31267589627236.3628198651263017.36823148627875.251708761
#Sta/Elev= 30
9740.60934.820029758.13529.611299769.27725.07219 9800.8724.36164 9814.9117.90177
9832.46212.935969853.52310.149489888.6253.3289089944.7890.0206359948.299  -0.999
10007.97  -0.99910025.520.43036510032.540.14504410036.06  -0.999 10085.2  -0.999
10106.260.34239710113.28-0.4793610137.850.04854110141.36  -0.99910194.02  -0.999
10197.53 0.02317 10222.10.23293410253.69-0.6628910274.750.27119510285.28  -0.999
10306.342.44854810348.6613.1797910373.0417.4230210394.7923.1495410424.1725.59514
#Mann= 3 , 0 , 0
9740.609    0.03       09740.609    0.03       010424.17    0.03       0
#XS Ineff= 2 , 0
       0                               0
Bank Sta=9740.609,10424.17
Exp/Cntr=0.3,0.1

Type RM Length L Ch R = 1 ,125.6515,0.000000,0.000000,0.000000
XS GIS Cut Line= 2
1262175.11924425 627438.782524721262867.82757756628087.220024735
#Sta/Elev= 30
 9694.6424.528889710.52220.142669746.47416.736819778.50811.03762 9855.32 1.97773
9903.328  -0.99910004.15  -0.99910008.950.13552910065.55  -0.99910085.760.783455
10100.16-0.6336710114.560.36540210137.45  -0.99910146.440.31391110164.41  -0.999
10181.771.25250410195.87  -0.99910209.35  -0.99910215.380.52492110227.33  -0.999
 10306.6  -0.999 10330.60.46862810388.21  -0.99910393.010.21718410438.550.513623
10508.23  -0.99910532.920.97838410568.878.69960810600.3311.4961910643.49 19.5853
#Mann= 3 , 0 , 0
 9694.64    0.03       0 9694.64    0.03       010643.49    0.03       0
#XS Ineff= 2 , 0
       09972.794        10217.48       0
Bank Sta=9694.64,10643.49
Exp/Cntr=0.3,0.1